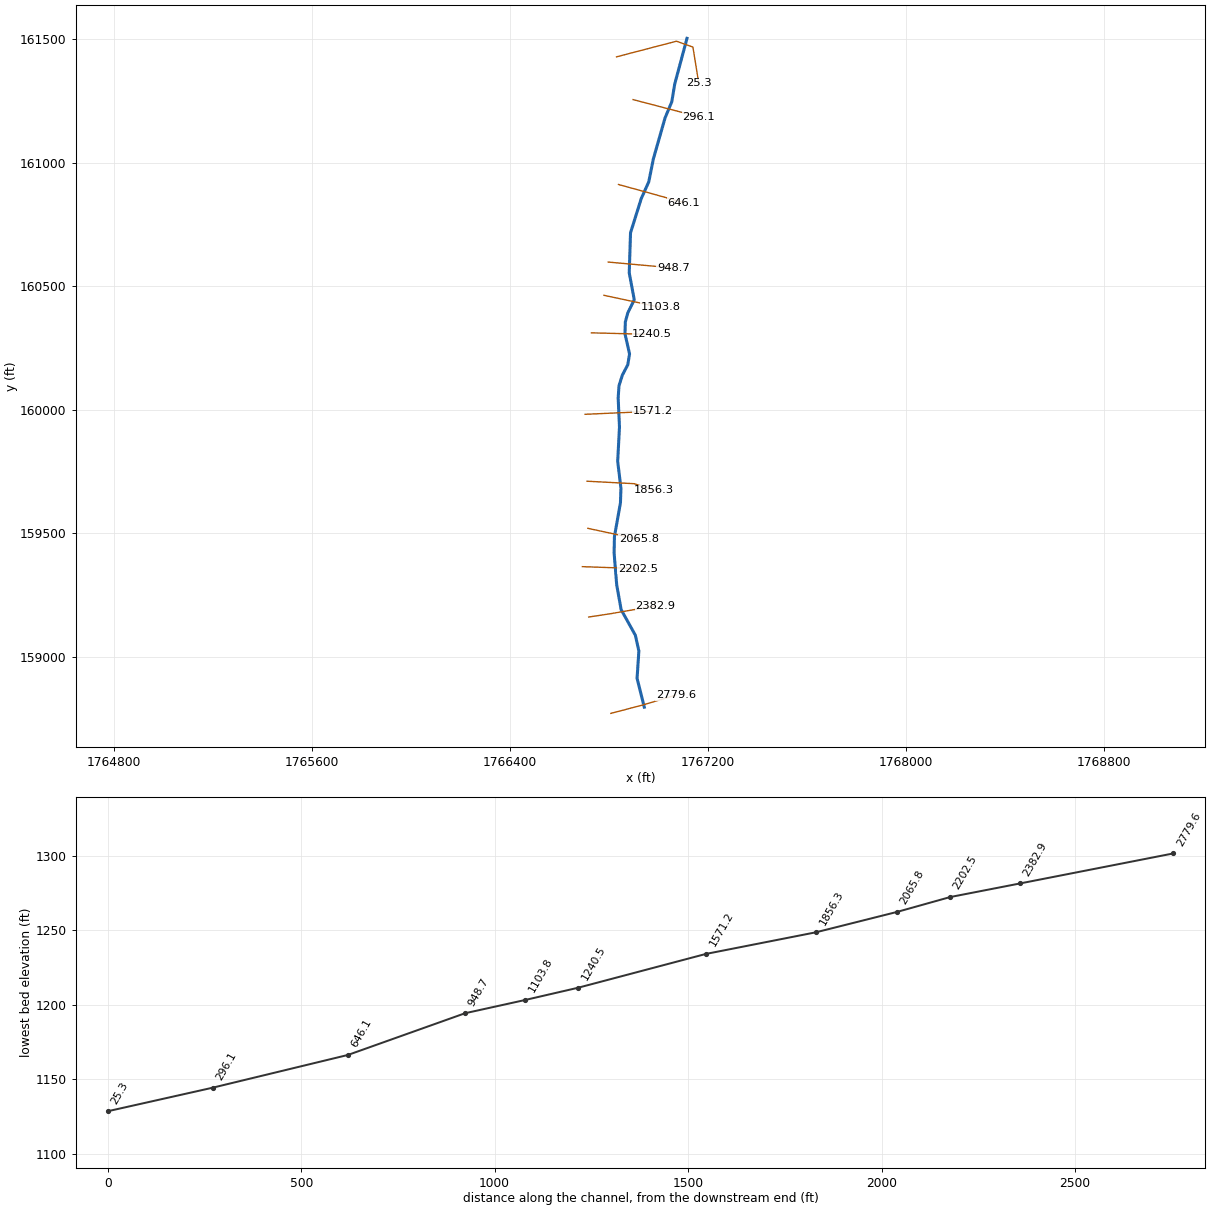
--- Spice Laurel Branch.prj (project) ---

Proj Title=Spice Laurel Branch
Current Plan=p01
Default Exp/Contr=0,0
English Units
Geom File=g01
Flow File=f01
Plan File=p01
BEGIN DESCRIPTION:
END DESCRIPTION:
DSS Export Rating Curves= 0
DSS Export Rating Curve Sorted= 0
DSS Export Volume Flow Curves= 0
DXF OffsetX= 0
DXF OffsetY= 0
DXF ScaleX= 0
DXF ScaleY= 0

--- Spice Laurel Branch.p01 (plan) ---

Plan Title=Floodplain
Program Version=4.00
Geom File=g01
Flow File=f01
K Sum by GR=0
Std Step Tol=0.01
Critical Tol=0.01
Num of Std Step Trials=20
Max Error Tol=0.3
Flow Tol Ratio=0.001
Split Flow NTrial=30
Split Flow Tol=0.02
Split Flow Ratio=0.02
Log Output Level=0
Friction Slope Method=1
Unsteady Friction Slope Method=2
Unsteady Bridges Friction Slope Method=1
Global Log Level=0
CheckData=False
Run HTab=0
Run UNet=0
Run PostProcess=0
UNET Theta=0
UNET Theta Warmup=0
UNET ZTol=0
UNET ZSATol=0
UNET MxIter=0
UNET MaxInSteps=0
UNET DtIC=0
UNET DtMin=0
UNET MaxCRTS=0
UNET WFStab=0
UNET SFStab=0
UNET WFX=0
UNET SFX=0
UNET DSS MLevel=0
UNET DZMax Abort=0
UNET Convert EG Bridges=0
UNET Use Existing IB Tables=0
UNET Froude Limit=0
UNET Froude Power=0
Write IC File=0
Echo Input=False
Echo Output=False
Write Detailed=0

--- Spice Laurel Branch.f01 (steady flow) ---

Flow Title=NFF Regression Equation
Program Version=4.00
Number of Profiles=1
Profile Names=P100yr
River Rch & RM=Spice Laurel ...,Main      ,2779.6
548.0300
River Rch & RM=Spice Laurel ...,Main      ,2382.9
548.4462
River Rch & RM=Spice Laurel ...,Main      ,2382.9
614.2419
River Rch & RM=Spice Laurel ...,Main      ,296.1
667.1866
Boundary for River Rch & Prof#=Spice Laurel ...,Main      ,1
Up Type=0
Dn Type=3
Dn Slope=0.071423

--- Spice Laurel Branch.g01 (geometry) ---

Geom Title=Geometry
Program Version=4.00

River Reach=Spice Laurel ...     ,Main
Reach XY= 30
     1766941.385      158796.958     1766912.261      158913.591
     1766919.580      159024.222     1766905.223      159088.350
     1766847.935      159191.662     1766830.045      159291.782
     1766819.538      159421.143     1766820.852      159487.466
     1766845.148      159624.051     1766847.118      159683.150
     1766833.985      159792.155     1766841.208      159930.710
     1766835.955      160048.251     1766839.238      160098.158
     1766853.028      160141.497     1766874.697      160182.866
     1766881.921      160226.863     1766863.534      160308.288
     1766864.848      160356.224     1766874.697      160392.997
     1766900.964      160446.186     1766880.650      160555.132
     1766885.861      160717.386     1766929.200      160855.941
     1766959.757      160924.488     1766978.249      161017.211
     1767025.072      161181.643     1767052.604      161247.971
     1767064.319      161319.219     1767114.003      161504.630

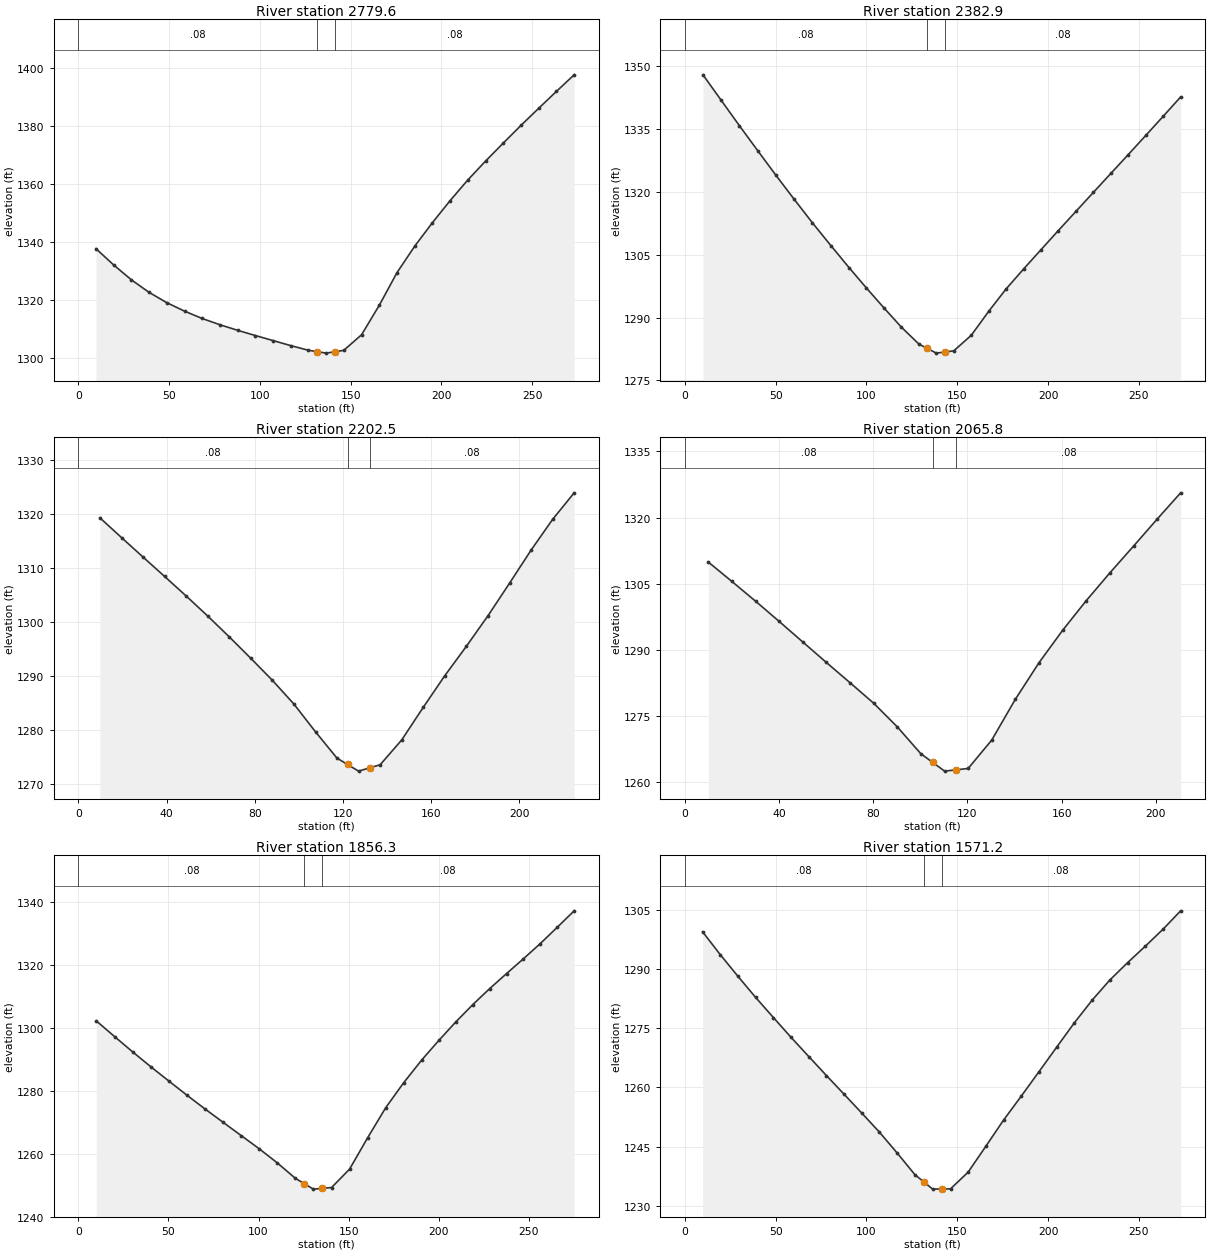
Type RM Length L Ch R = 1 ,2779.6,398.6,396.7,394.2
XS GIS Cut Line= 3
     1766806.539      158771.706     1766938.508      158806.515
     1767069.319      158845.852
#Sta/Elev= 30
     9.7 1337.70    19.5 1332.06    29.2 1326.96    39.0 1322.61    48.7 1319.07
    58.5 1316.14    68.2 1313.61    78.0 1311.45    87.7 1309.54    97.5 1307.73
   107.2 1306.00   117.0 1304.25   126.7 1302.65   131.5 1302.17   136.5 1301.66
   141.5 1302.15   146.2 1302.62   156.0 1307.99   165.8 1318.21   175.5 1329.41
   185.3 1338.57   195.0 1346.64   204.8 1354.29   214.5 1361.38   224.3 1367.91
   234.1 1374.15   243.8 1380.22   253.6 1386.14   263.3 1391.94   273.1 1397.67
#Mann= 3 , 0 , 0
       0    0.08       0   131.5   0.045       0   141.5    0.08       0
Bank Sta=   131.5,   141.5
Exp/Cntr=0.3,0.1

Type RM Length L Ch R = 1 ,2382.9,184.4,180.4,176.3
XS GIS Cut Line= 3
     1766716.819      159161.728     1766806.204      159175.374
     1766986.104      159206.609
#Sta/Elev= 30
    10.0 1347.93    20.1 1341.82    30.1 1335.77    40.2 1329.80    50.2 1323.94
    60.3 1318.18    70.3 1312.59    80.4 1307.19    90.4 1301.93   100.0 1297.05
   109.6 1292.32   119.3 1287.68   128.9 1283.66   133.5 1282.63   138.5 1281.50
   143.5 1281.79   148.1 1282.05   157.7 1285.74   167.3 1291.46   176.9 1296.82
   186.5 1301.56   196.1 1306.18   205.7 1310.77   215.4 1315.35   225.0 1319.89
   234.6 1324.40   244.2 1328.91   253.8 1333.45   263.4 1338.03   273.0 1342.65
#Mann= 3 , 0 , 0
       0    0.08       0   133.5   0.045       0   143.5    0.08       0
Bank Sta=   133.5,   143.5
Exp/Cntr=0.3,0.1

Type RM Length L Ch R = 1 ,2202.5,140.3,136.8,133.2
XS GIS Cut Line= 2
     1766691.474      159365.714     1766916.251      159357.800
#Sta/Elev= 25
     9.8 1319.34    19.6 1315.68    29.3 1312.09    39.1 1308.49    48.9 1304.86
    58.7 1301.13    68.5 1297.26    78.2 1293.31    88.0 1289.23    97.8 1284.81
   107.6 1279.66   117.3 1274.80   122.1 1273.61   127.1 1272.38   132.1 1272.98
   136.9 1273.56   146.7 1278.17   156.5 1284.24   166.2 1290.06   176.0 1295.52
   185.8 1301.18   195.6 1307.23   205.4 1313.38   215.1 1319.04   224.9 1323.98
#Mann= 3 , 0 , 0
       0    0.08       0   122.1   0.045       0   132.1    0.08       0
Bank Sta=   122.1,   132.1
Exp/Cntr=0.3,0.1

Type RM Length L Ch R = 1 ,2065.8,206.3,209.5,212.6
XS GIS Cut Line= 2
     1766713.635      159520.843     1766919.417      159476.520
#Sta/Elev= 23
    10.0 1309.89    20.0 1305.49    30.1 1300.99    40.1 1296.41    50.1 1291.75
    60.1 1287.11    70.2 1282.48    80.2 1277.85    90.2 1272.49   100.2 1266.40
   105.3 1264.40   110.3 1262.44   115.3 1262.74   120.3 1263.05   130.3 1269.48
   140.3 1278.72   150.4 1287.07   160.4 1294.40   170.4 1301.12   180.4 1307.40
   190.5 1313.51   200.5 1319.62   210.5 1325.61
#Mann= 3 , 0 , 0
       0    0.08       0   105.3   0.045       0   115.3    0.08       0
Bank Sta=   105.3,   115.3
Exp/Cntr=0.3,0.1

Type RM Length L Ch R = 1 ,1856.3,283.1,285.1,287.1
XS GIS Cut Line= 3
     1766710.615      159711.588     1766901.001      159701.562
     1766981.146      159674.954
#Sta/Elev= 30
    10.0 1302.22    20.1 1297.26    30.1 1292.41    40.1 1287.72    50.2 1283.14
    60.2 1278.65    70.2 1274.29    80.3 1270.03    90.3 1265.82   100.3 1261.63
   110.4 1257.11   120.4 1252.23   125.4 1250.50   130.4 1248.78   135.4 1249.03
   140.5 1249.29   150.5 1255.14   160.5 1265.09   170.6 1274.70   180.6 1282.66
   190.6 1289.86   200.0 1296.02   209.4 1301.89   218.8 1307.38   228.2 1312.48
   237.6 1317.28   246.9 1321.95   256.3 1326.80   265.7 1331.97   275.1 1337.21
#Mann= 3 , 0 , 0
       0    0.08       0   125.4   0.045       0   135.4    0.08       0
Bank Sta=   125.4,   135.4
Exp/Cntr=0.3,0.1

Type RM Length L Ch R = 1 ,1571.2,332.1,330.7,329.2
XS GIS Cut Line= 3
     1766702.261      159982.471     1766838.625      159988.559
     1766974.989      159994.647
#Sta/Elev= 30
     9.8 1299.38    19.5 1293.60    29.3 1288.08    39.0 1282.76    48.8 1277.65
    58.5 1272.65    68.3 1267.77    78.0 1262.97    87.8 1258.20    97.5 1253.45
   107.2 1248.63   117.0 1243.33   126.7 1237.88   131.5 1236.09   136.5 1234.22
   141.5 1234.26   146.3 1234.29   156.0 1238.52   165.8 1245.10   175.5 1251.69
   185.3 1257.79   195.0 1263.94   204.8 1270.19   214.5 1276.33   224.3 1282.07
   234.0 1287.15   243.8 1291.56   253.5 1295.70   263.3 1300.02   273.0 1304.68
#Mann= 3 , 0 , 0
       0    0.08       0   131.5   0.045       0   141.5    0.08       0
Bank Sta=   131.5,   141.5
Exp/Cntr=0.3,0.1

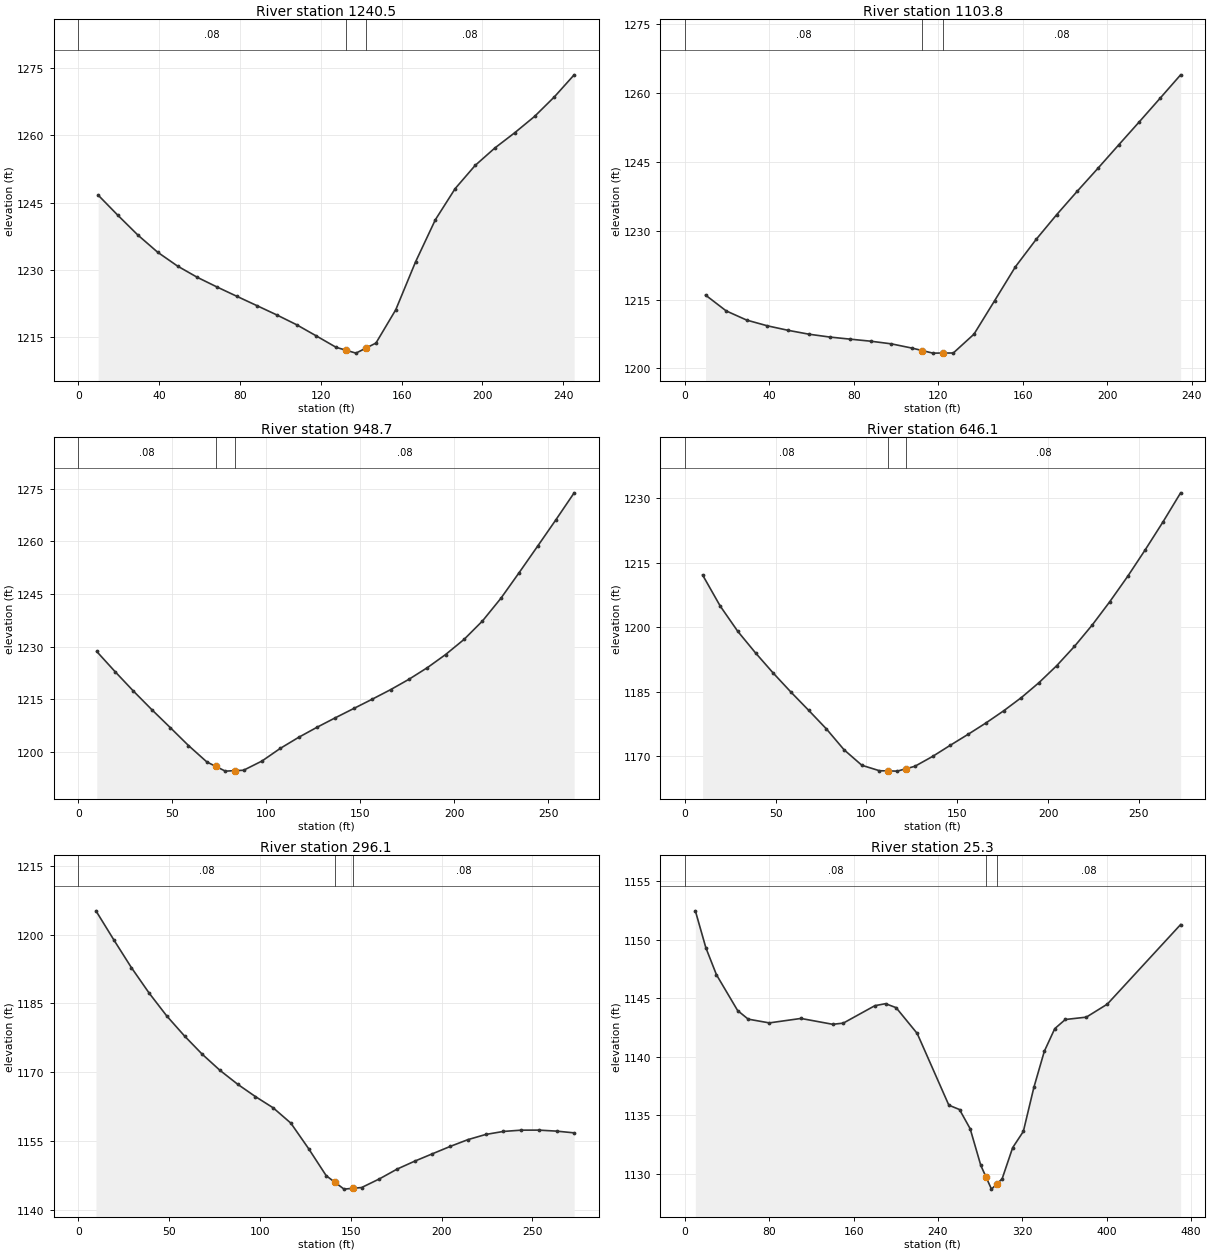
Type RM Length L Ch R = 1 ,1240.5,140.3,136.7,133.2
XS GIS Cut Line= 2
     1766727.881      160312.313     1766973.237      160305.982
#Sta/Elev= 27
     9.8 1246.70    19.6 1242.19    29.5 1237.79    39.3 1233.97    49.1 1230.90
    58.9 1228.39    68.7 1226.23    78.5 1224.16    88.4 1222.09    98.2 1220.03
   108.0 1217.85   117.8 1215.35   127.6 1212.81   132.4 1212.18   137.4 1211.52
   142.4 1212.65   147.3 1213.76   157.1 1221.17   166.9 1231.83   176.7 1241.21
   186.5 1248.14   196.4 1253.30   206.2 1257.20   216.0 1260.58   225.8 1264.21
   235.6 1268.56   245.4 1273.47
#Mann= 3 , 0 , 0
       0    0.08       0   132.4   0.045       0   142.4    0.08       0
Bank Sta=   132.4,   142.4
Exp/Cntr=0.3,0.1

Type RM Length L Ch R = 1 ,1103.8,152.5,155.1,157.8
XS GIS Cut Line= 2
     1766778.535      160464.276     1767008.062      160415.205
#Sta/Elev= 26
     9.8 1215.98    19.6 1212.52    29.3 1210.52    39.1 1209.27    48.9 1208.29
    58.7 1207.45    68.5 1206.83    78.2 1206.37    88.0 1205.92    97.8 1205.34
   107.6 1204.41   112.4 1203.88   117.4 1203.32   122.4 1203.34   127.1 1203.35
   136.9 1207.46   146.7 1214.78   156.5 1222.14   166.3 1228.10   176.0 1233.48
   185.8 1238.62   195.6 1243.62   205.4 1248.71   215.2 1253.76   224.9 1258.82
   234.7 1263.97
#Mann= 3 , 0 , 0
       0    0.08       0   112.4   0.045       0   122.4    0.08       0
Bank Sta=   112.4,   122.4
Exp/Cntr=0.3,0.1

Type RM Length L Ch R = 1 ,948.7,306.2,302.6,299
XS GIS Cut Line= 2
     1766795.948      160598.826     1767058.716      160575.082
#Sta/Elev= 29
     9.8 1228.58    19.5 1222.86    29.3 1217.29    39.1 1211.98    48.9 1206.87
    58.6 1201.75    68.4 1197.05    73.2 1195.77    78.2 1194.44    83.2 1194.57
    87.9 1194.69    97.7 1197.32   107.5 1200.95   117.3 1204.11   127.0 1206.96
   136.8 1209.68   146.6 1212.33   156.3 1214.95   166.1 1217.68   175.9 1220.65
   185.7 1223.97   195.4 1227.71   205.2 1232.02   215.0 1237.28   224.8 1243.75
   234.5 1251.06   244.3 1258.59   254.1 1266.18   263.8 1273.86
#Mann= 3 , 0 , 0
       0    0.08       0    73.2   0.045       0    83.2    0.08       0
Bank Sta=    73.2,    83.2
Exp/Cntr=0.3,0.1

Type RM Length L Ch R = 1 ,646.1,349.7,350,350.2
XS GIS Cut Line= 3
     1766837.239      160912.903     1766968.853      160876.709
     1767100.232      160839.661
#Sta/Elev= 30
     9.8 1212.17    19.5 1204.93    29.2 1199.02    39.0 1193.99    48.7 1189.31
    58.5 1184.86    68.2 1180.64    78.0 1176.29    87.7 1171.44    97.5 1167.83
   107.2 1166.56     112 1166.52   117.0 1166.47     122 1167.05   126.7 1167.60
   136.5 1169.91   146.2 1172.50   156.0 1175.05   165.8 1177.69   175.5 1180.50
   185.3 1183.60   195.0 1187.08   204.8 1191.05   214.5 1195.51   224.3 1200.50
   234.0 1205.95   243.8 1211.82   253.5 1218.03   263.3 1224.54   273.0 1231.31
#Mann= 3 , 0 , 0
       0    0.08       0     112   0.045       0     122    0.08       0
Bank Sta=     112,     122
Exp/Cntr=0.3,0.1

Type RM Length L Ch R = 1 ,296.1,272.5,270.8,269
XS GIS Cut Line= 3
     1766895.958      161256.636     1767028.005      161222.052
     1767160.051      161187.469
#Sta/Elev= 30
     9.7 1205.22    19.5 1198.91    29.2 1192.84    39.0 1187.26    48.7 1182.27
    58.5 1177.89    68.2 1173.93    78.0 1170.40    87.8 1167.35    97.5 1164.68
   107.3 1162.22   117.0 1158.89   126.8 1153.31   136.5 1147.40   141.2 1146.00
   146.3 1144.48   151.2 1144.66   156.0 1144.83   165.8 1146.72   175.5 1148.85
   185.3 1150.60   195.0 1152.20   204.8 1153.81   214.5 1155.28   224.3 1156.41
   234.0 1157.07   243.8 1157.35   253.5 1157.36   263.3 1157.14   273.0 1156.76
#Mann= 3 , 0 , 0
       0    0.08       0   141.2   0.045       0   151.2    0.08       0
Bank Sta=   141.2,   151.2
Exp/Cntr=0.3,0.1

Type RM Length L Ch R = 1 ,25.3,24.5,25.3,26.1
XS GIS Cut Line= 4
     1766829.249      161429.639     1767071.439      161492.956
     1767137.923      161469.212     1767161.667      161321.999
#Sta/Elev= 30
    10.0 1152.45    20.0 1149.29    30.0 1147.00    50.1 1143.94    60.1 1143.21
    80.1 1142.89   110.1 1143.27   140.2 1142.77   150.2 1142.87   180.2 1144.36
   190.3 1144.53   200.3 1144.19   220.3 1141.99   250.3 1135.87   260.4 1135.50
   270.5 1133.86   280.6 1130.73   285.7 1129.71   290.7 1128.71   295.7 1129.14
   300.8 1129.59   310.8 1132.25   320.9 1133.63   330.9 1137.39   340.8 1140.47
   350.7 1142.40   360.7 1143.18   380.6 1143.38   400.5 1144.49   470.0 1151.28
#Mann= 3 , 0 , 0
       0    0.08       0   285.7   0.045       0   295.7    0.08       0
Bank Sta=   285.7,   295.7
Exp/Cntr=0.3,0.1